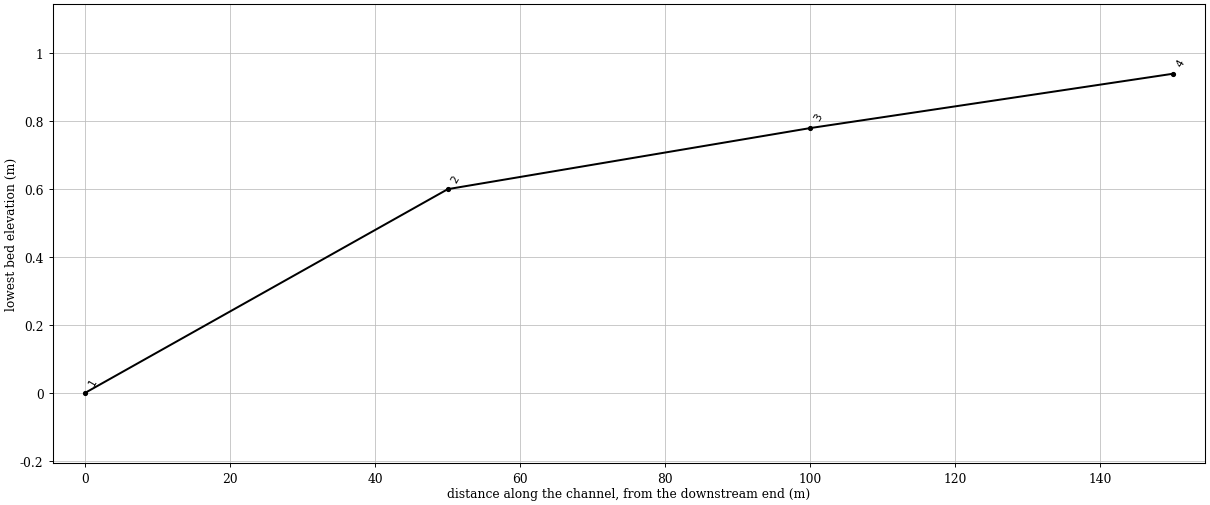
--- project4.prj (project) ---

Proj Title=project 4
Current Plan=p01
Default Exp/Contr=0.3,0.1
SI Units
Geom File=g01
Flow File=f01
Plan File=p01
Y Axis Title=Elevation
X Axis Title(PF)=Main Channel Distance
X Axis Title(XS)=Station
BEGIN DESCRIPTION:
END DESCRIPTION:
DSS Export Rating Curves= 0
DSS Export Rating Curve Sorted= 0
DSS Export Volume Flow Curves= 0
DXF OffsetX= 0
DXF OffsetY= 0
DXF ScaleX= 1
DXF ScaleY= 10

--- project4.p01 (plan) ---

Plan Title=Plan 01
Program Version=6.60
Short Identifier=pl09
Geom File=g01
Flow File=f01
Mixed Flow
K Sum by GR= 0
Std Step Tol= 0.003
Critical Tol= 0.003
Num of Std Step Trials= 20
Max Error Tol= 0.1
Flow Tol Ratio= 0.001
Split Flow NTrial= 30
Split Flow Tol= 0.006
Split Flow Ratio= 0.02
Log Output Level= 0
Friction Slope Method= 1
Unsteady Friction Slope Method= 2
Unsteady Bridges Friction Slope Method= 1
Parabolic Critical Depth
Global Vel Dist= 0 , 0 , 0
Global Log Level= 0
CheckData=True
Encroach Param=-1 ,0,0, 0
Flow Ratio Tolerance=0.1
Flow Ratio Min Ratio=0.5
Flow Ratio Max Ratio=4
Flow Ratio Max Iterations= 10
Computation Interval=1MIN
Output Interval=1HOUR
Instantaneous Interval=1HOUR
Mapping Interval=1HOUR
Computation Time Step Use Courant=        0
Computation Time Step Use Time Series=    0
Computation Time Step Count To Double=0
Computation Time Step Max Doubling=0
Computation Time Step Max Halving=0
Computation Time Step Residence Courant=0
Run HTab= 0
Run UNet= 0
Run Sediment= 0
Run PostProcess= 0
Run WQNet= 0
Run RASMapper= 0
UNET Theta= 1
UNET Theta Warmup= 1
UNET ZTol= 0.006
UNET ZSATol= 0.006
UNET MxIter= 20
UNET Max Iter WO Improvement= 0
UNET MaxInSteps= 0
UNET DtIC= 0
UNET DtMin= 0
UNET MaxCRTS= 20
UNET WFStab= 2
UNET SFStab= 1
UNET WFX= 1
UNET SFX= 1
UNET Gravity=9.80665
UNET 1D Methodology=Finite Difference
UNET DSS MLevel= 4
UNET Pardiso=0
UNET DZMax Abort= 30
UNET Use Existing IB Tables=-1
UNET Froude Reduction=False
UNET Froude Limit= 0.8
UNET Froude Power= 4
UNET D1 Cores= 0
UNET WindReference=Eulerian
UNET WindDragFormulation=Hsu (1988)
UNET D2 Coriolis=0
UNET D2 Cores= 0
UNET D2 Theta= 1
UNET D2 Theta Warmup= 1
UNET D2 Z Tol= 0.003
UNET D2 Volume Tol= 0.003
UNET D2 Max Iterations= 20
UNET D2 Advanced Convergence=0
UNET D2 WS Max Tol=0.045
UNET D2 WS RMS Tol=0.006
UNET D2 WS Stall Tol=1
UNET D2 Equation= 0
UNET D2 RampUpFraction=0.1
UNET D2 TimeSlices= 1
UNET D2 Turbulence Formulation=None
UNET D2 Eddy Viscosity=0.3
UNET D2 Transverse Eddy Viscosity=0.1
UNET D2 Smagorinsky Mixing=0.05
UNET D2 BCVolumeCheck=0
UNET D2 Cores=0
UNET D2 SolverType=PARDISO (Direct)
UNET D2 Minimum Iterations= 3
UNET D2 Maximum Iterations= 30
UNET D2 Restart Number= 10
UNET D2 Relaxation Coeff=1.3
UNET D2 SOR Precondition Iterations= 10
UNET D2 ILUT Maximum Fill= 8
UNET D2 ILUT Tolerance=1E-08
UNET D2 Convergence Tolerance=0.00001
PS Theta= 1
PS WS Tol= 0.003
PS Volume Tol= 0.003
PS Max Iterations= 20
PS Equation= 0
PS Advance Time Step=-1
PS Target Courant=0.9
PS Time Slices= 1
PS Iterate With 2D=0
PS Project Initial WSE from DS=-1
PS Ramp Up Initial WSE from US=-1
PS Cores=0
UNET D1D2 MaxIter= 0
UNET D1D2 ZTol=0.003
UNET D1D2 QTol=0.1
UNET D1D2 MinQTol=0.03
Write IC File= 0
Write IC File at Fixed DateTime=0
Write IC File at Sim End=0
Echo Input=False
Echo Parameters=False
Echo Output=False
Write Detailed= 0
HDF Write Warmup=0
HDF Write Time Slices=0
HDF Flush=0
HDF Compression= 1
HDF Chunk Size= 1
HDF Spatial Parts= 1
HDF Use Max Rows=0
HDF Fixed Rows= 1
Calibration Method= 0
Calibration Iterations= 20
Calibration Max Change=0.05
Calibration Tolerance=0.2
Calibration Maximum=1.5
Calibration Minimum=0.5
Calibration Optimization Method= 1
WQ AD Non Conservative
WQ ULTIMATE=-1
WQ Max Comp Step=1HOUR
WQ Output Interval=15MIN
WQ Output Selected Increments= 0
WQ Create Restart=0
WQ Fixed Restart=0
WQ System Summary=0
WQ Write To DSS=0
Sorting and Armoring Iterations= 10
XS Update Threshold= 0.02
Bed Roughness Predictor= 0
Processes Affected by Predictor=Sediment Only
Hydraulics Update Threshold= 0.02
Energy Slope Method= 1
Volume Change Method= 1
Sediment Retention Method= 0
Sediment TS Multiplier= 1
Warm Up Method= 0
XS Weighting Method= 0
Number of US Weighted Cross Sections= 1
Number of DS Weighted Cross Sections= 1
Upstream XS Weight=0
Main XS Weight=1
Downstream XS Weight=0
Number of DS XS's Weighted with US Boundary= 1
Upstream Boundary Weight= 1
Weight of XSs Associated with US Boundary= 0
Number of US XS's Weighted with DS Boundary= 1
Downstream Boundary Weight= 0.5
Weight of XSs Associated with DS Boundary= 0.5
Percentile Method= 0
Sediment Output Level= 3
Mass or Volume Output= 0
Output Increment Type= 1
Profile and TS Output Increment= 1
Transport Output Increment 1
XS Output Flag= 0
XS Output Increment= 10
Read HDF5 Sediment Hotstart= 0
Sediment Hotstart Type= 0
Write Gradation File= 0
Read Gradation Hotstart= 0
Write HDF5 File= 1
Write Binary Output= 1
Write DSS Sediment File= 0
DSS Sediment Output Type= 1
SV Curve= 0
Specific Gage Flag= 0
Subcell Erosion Methods= 0
Subcell Deposition Methods= 0
Advection Scheme= 1
Matrix Solver= 0
Implicit Weighting Factor= 1
Maximum Outer Loop Convergence Iterations= 5
Convergence Maximum Absolute= 0.001
Convergence RMSE= 0.0001
Grain Fractions Max Abs Error= 0.001
Max Subgrid Regions= 1
Max Subgrid Length Scale= 3.402823E+38
Initial Layer Thickness= 3
Min Layer Thickness= 0.1
Max Layer Thickness= 6
Number of Layers= 5

--- project4.f01 (steady flow) ---

Flow Title=flow4
Program Version=6.60
Number of Profiles= 1
Profile Names=PF 1
River Rch & RM=river,600 m           ,4
      10
Boundary for River Rch & Prof#=river,600 m           , 1
Up Type= 3
Up Slope=0.0008
Dn Type= 2
DSS Import GetInterval= 0
DSS Import GetPeak= 0
DSS Import FillOption= 0

--- project4.g01 (geometry) ---

Geom Title=geometry4
Program Version=6.60

River Reach=river           ,600 m
Reach XY= 2
-0.44709543568460.867219917012451.216804979253110.41078838174274

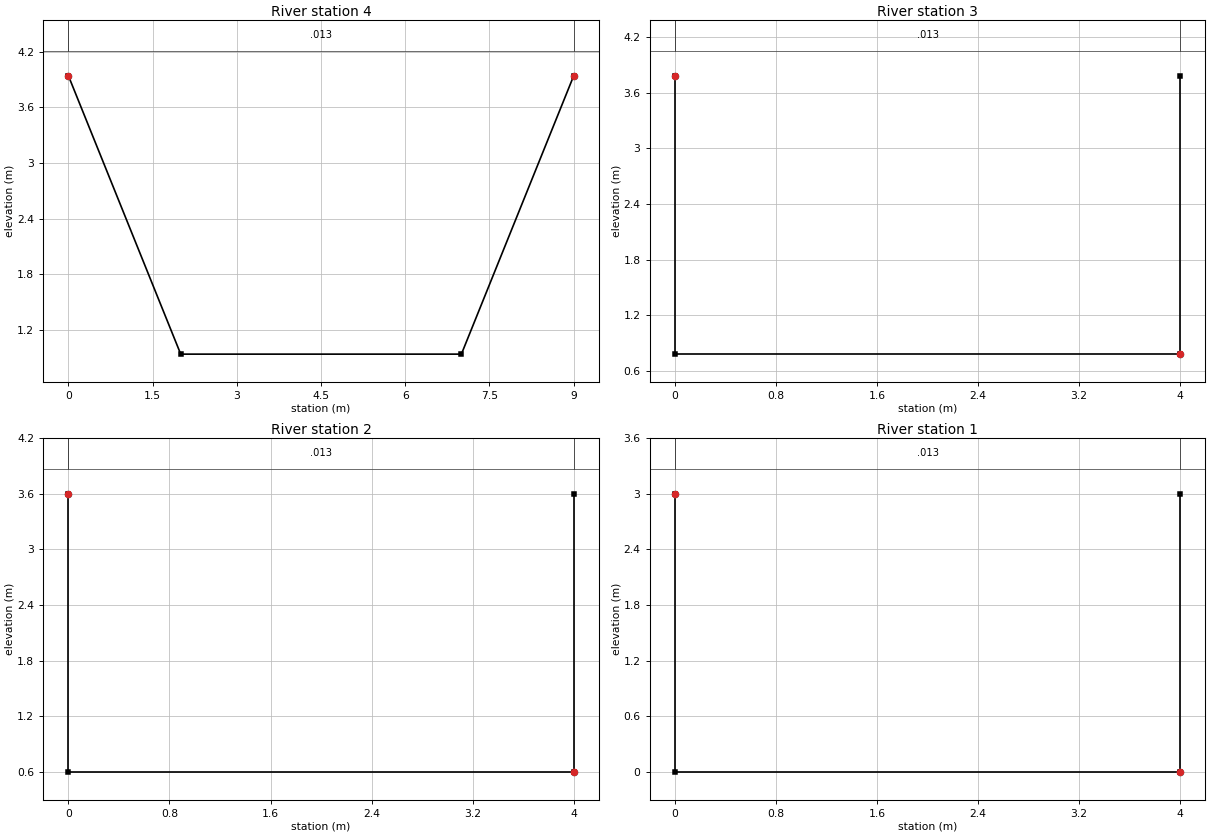
Type RM Length L Ch R = 1 ,4       ,50,50,50
BEGIN DESCRIPTION:
upstream
END DESCRIPTION:
#Sta/Elev= 4
       0    3.94       2     .94       7     .94       9    3.94
#Mann= 3 ,0,0
       0    .013       0       0    .013       0       9    .013       0
Bank Sta=0,9
XS Rating Curve= 0 ,0
Exp/Cntr=0.3,0.1

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
Type RM Length L Ch R = 1 ,3       ,50,50,50
BEGIN DESCRIPTION:
uprec
END DESCRIPTION:
#Sta/Elev= 4
       0    3.78       0     .78       4     .78       4    3.78
#Mann= 3 ,0,0
       0    .013       0       0    .013       0       4    .013       0
Bank Sta=0,4
XS Rating Curve= 0 ,0
Exp/Cntr=0.3,0.1

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
Type RM Length L Ch R = 1 ,2       ,50,50,50
BEGIN DESCRIPTION:
downrec
END DESCRIPTION:
#Sta/Elev= 4
       0     3.6       0      .6       4      .6       4     3.6
#Mann= 3 ,0,0
       0    .013       0       0    .013       0       4    .013       0
Bank Sta=0,4
XS Rating Curve= 0 ,0
Exp/Cntr=0.3,0.1

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
Type RM Length L Ch R = 1 ,1       ,0,0,0
BEGIN DESCRIPTION:
downstream
END DESCRIPTION:
#Sta/Elev= 4
       0       3       0       0       4       0       4       3
#Mann= 3 ,0,0
       0    .013       0       0    .013       0       4    .013       0
Bank Sta=0,4
XS Rating Curve= 0 ,0
Exp/Cntr=0.3,0.1
LCMann Table=0

Chan Stop Cuts=-1
Use User Specified Reach Order=0
Composite Channel Slope=5